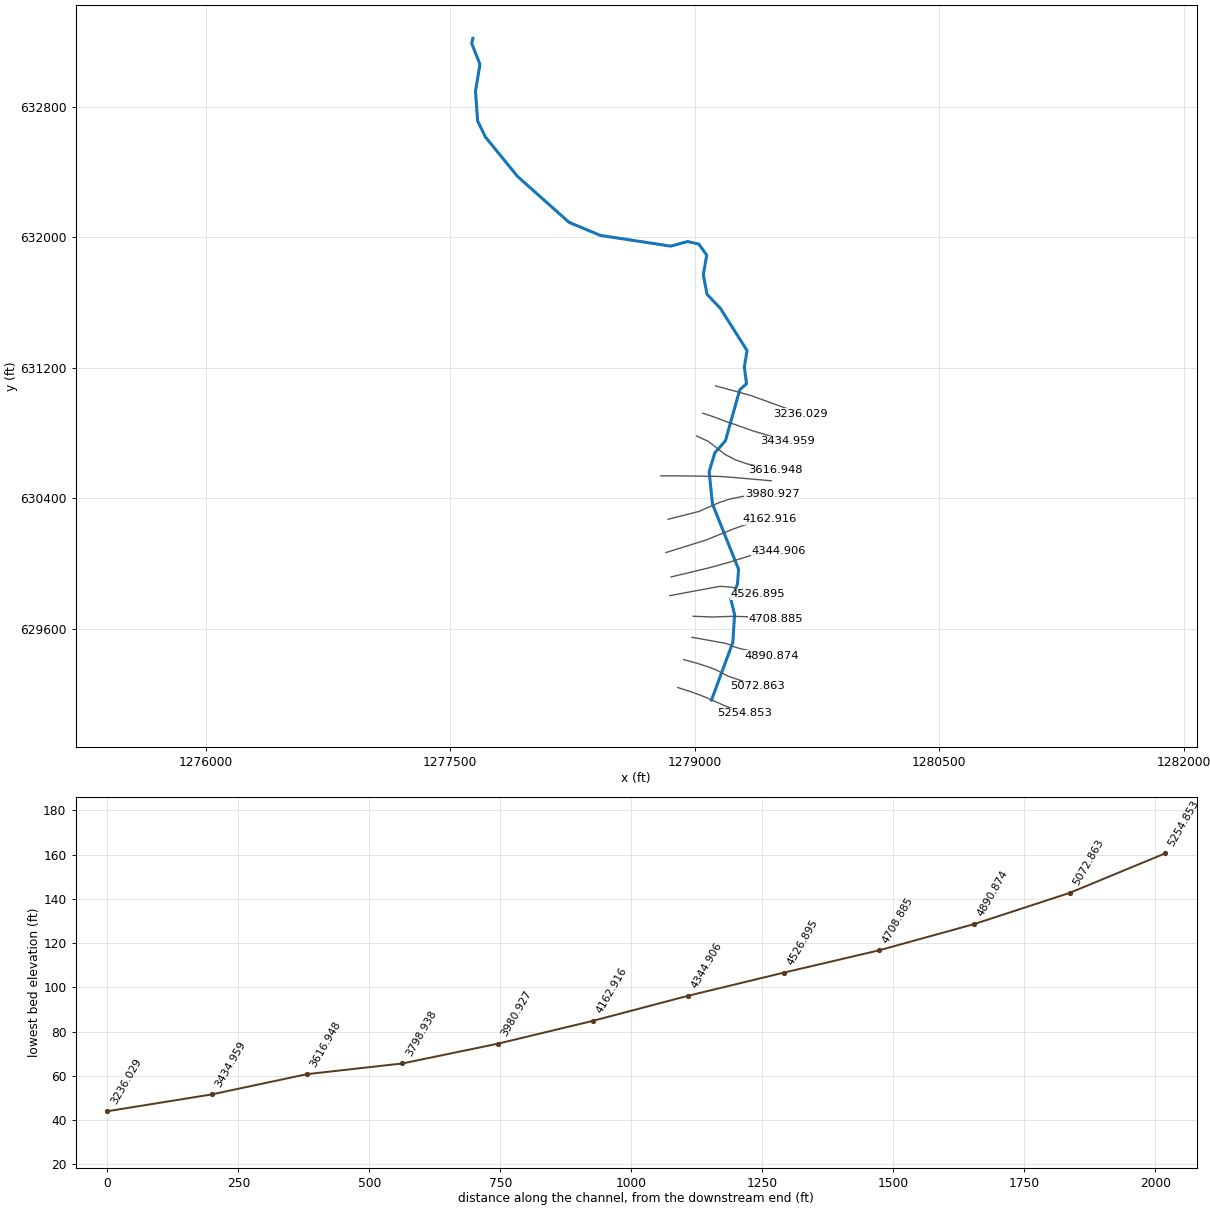
--- 756_ras.prj (project) ---

Proj Title=756
Current Plan=p01
Default Exp/Contr=0.3,0.1
English Units
Geom File=g01
Flow File=f01
Plan File=p01
Y Axis Title=Elevation
X Axis Title(PF)=Main Channel Distance
X Axis Title(XS)=Station
BEGIN DESCRIPTION:
RFD model 756 exported to HEC-RAS
END DESCRIPTION:

--- 756_ras.p01 (plan) ---

Plan Title=Plan 01
Program Version=4.10
Short Identifier=Plan 01
Geom File=g01
Flow File=f01
Subcritical Flow
Calc Critical at every XS
Secant Critical Depth

--- 756_ras.f01 (steady flow) ---

Flow Title=Flow 01
Program Version=5.01
Number of Profiles= 5
Profile Names=10yr,25yr,50yr,100yr,500yr
River Rch & RM=756,12,5254.853
  399.79  479.76  572.73  614.57  726.25
River Rch & RM=756,12,5072.863
  433.32  526.16   629.8  683.91  820.63
River Rch & RM=756,12,4890.874
  447.64  546.13  654.41  714.07  862.12
River Rch & RM=756,12,4708.885
   451.8  551.95  661.59  722.89   874.3
River Rch & RM=756,12,4526.895
  462.62  567.13  680.32  745.96  906.26
River Rch & RM=756,12,4344.906
  474.99  584.54  701.81  772.54  943.26
River Rch & RM=756,12,4162.916
  500.11  620.11   745.8  827.23 1019.97
River Rch & RM=756,12,3980.927
  510.55  634.97  764.19  850.23 1052.45
River Rch & RM=756,12,3798.938
  521.23  650.21  783.08  873.92 1086.02
River Rch & RM=756,12,3616.948
  534.26  668.87  806.21  903.02 1127.45
River Rch & RM=756,12,3434.959
  537.96   674.2  812.81  911.35 1139.34
River Rch & RM=756,12,3236.029
  541.63  679.47  819.35  919.61 1151.16
Boundary for River Rch & Prof#=756,12,1
Up Type= 0
Dn Type= 2
Boundary for River Rch & Prof#=756,12,2
Up Type= 0
Dn Type= 2
Boundary for River Rch & Prof#=756,12,2
Up Type= 0
Dn Type= 2
Boundary for River Rch & Prof#=756,12,2
Up Type= 0
Dn Type= 2
Boundary for River Rch & Prof#=756,12,2
Up Type= 0
Dn Type= 2

--- 756_ras.g01 (geometry) ---

Geom Title=756
Program Version=4.10

River Reach=756,12
Reach XY= 30
1279103.23052416629161.5097988461279234.06382925629514.843023459
1279244.89716443629685.6763057641279221.56384078629781.197018469
1279262.56679922629871.9603314551279269.51124367629963.626998127
1279109.06389111630364.8427748061279089.06390287 630563.17604984
1279124.06389593630678.176014688 1279189.0638789630752.342657415
1279276.56386224631064.0092289931279318.23051777631102.342549696
1279304.89719136631205.6758527761279321.56385603631304.842489517
1279159.06391158631562.3424178521279075.73060539631650.675727381
 1279053.2306156631770.6756924181279074.06394632631890.675656201
 1279025.7306292631958.1756375631278956.56398342631974.008968236
1278853.23067972631945.6756463411278421.56414235 632011.50897281
1278229.89753457632091.5089546871277914.96184621632372.049397174
1277717.32018729632614.1931655851277668.89143763632713.668442435
1277655.80259087632895.6034860431277683.28918504633060.523020851
1277632.24266583 633190.102657451277640.09597796633220.207016929

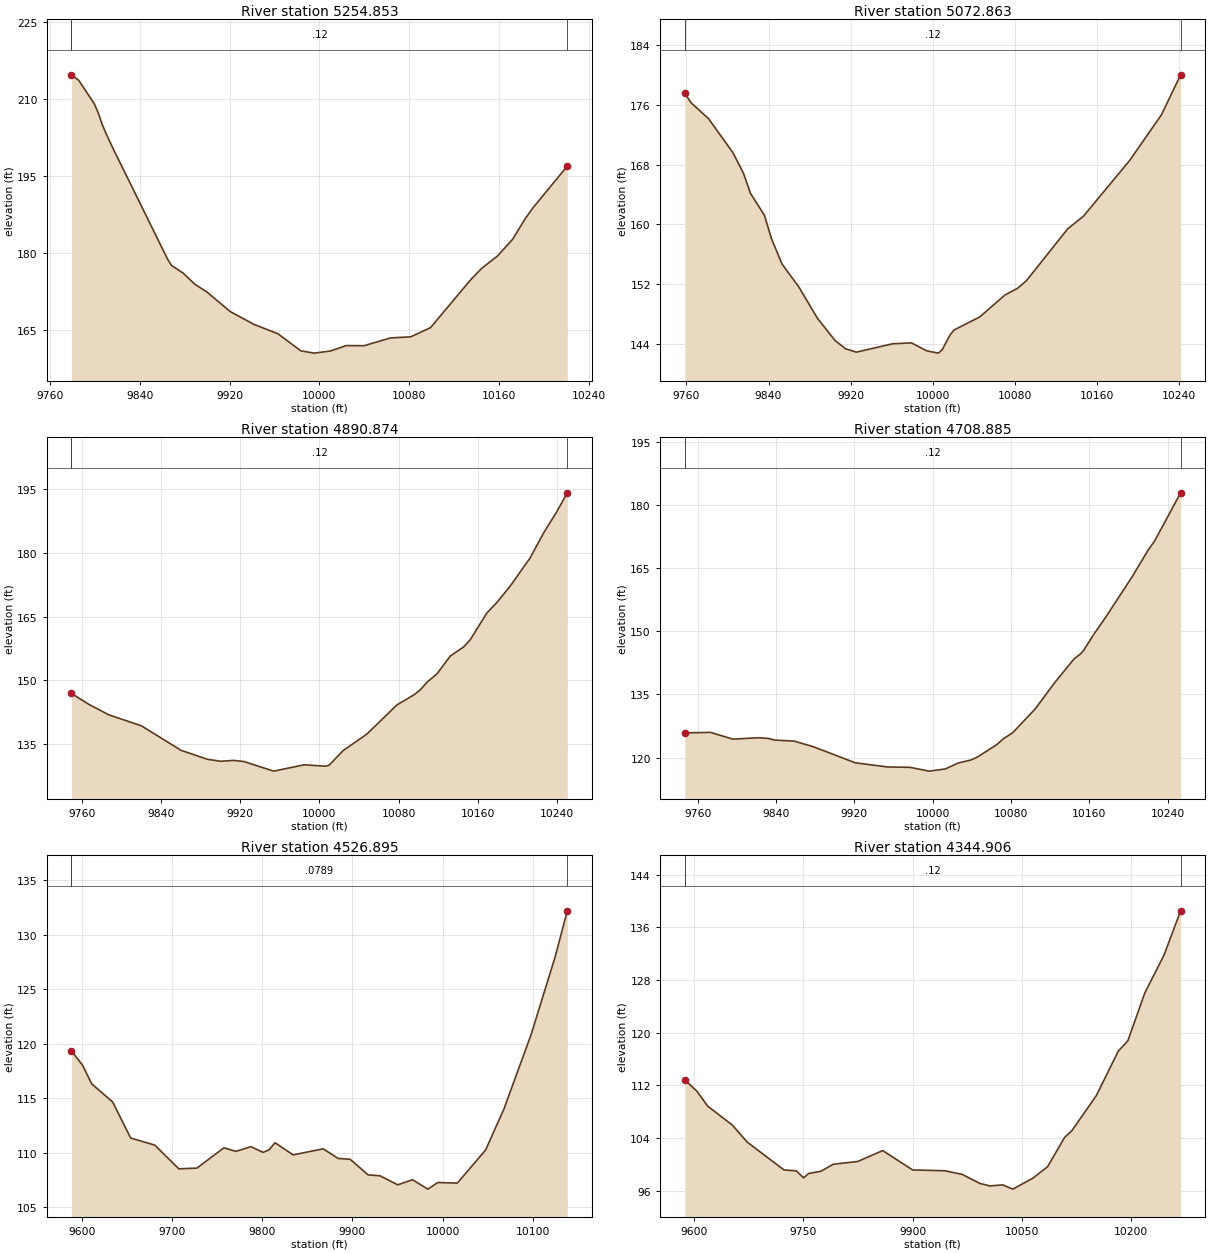
Type RM Length L Ch R = 1 ,5254.853,181.989400,181.989400,181.989400
XS GIS Cut Line= 6
1278896.39176856 629238.43898405 1278972.6868066629214.124481949
1279036.76353969629191.0374460721279077.62294244629174.413843893
1279184.07232717629127.0021593371279308.59272627629079.979272299
#Sta/Elev= 30
9779.025214.78649785.499213.71839799.272209.18769802.716207.48599806.159205.2785
9809.603203.47139816.489200.25719864.769178.85939868.256177.65329878.718176.1318
 9889.18173.96219899.641172.50079920.565168.66589941.713166.16729962.965164.3589
9983.505161.01639995.303160.5729 10009.7160.979210024.04162.044310039.79162.0186
10063.46163.536410081.39163.748110099.06165.537210135.23174.973110144.65177.0858
10158.68179.490510172.37182.788310183.23186.693110190.24188.845710220.96197.0078
#Mann= 3 , 0 , 0
9779.025    0.12       09779.025    0.12       010220.96    0.12       0
#XS Ineff= 2 , 0
       0                               0
Bank Sta=9779.025,10220.96
Exp/Cntr=0.3,0.1

Type RM Length L Ch R = 1 ,5072.863,181.989400,181.989400,181.989400
XS GIS Cut Line= 6
1278932.65732343629409.647315385 1279018.5629121629386.144996056
1279088.74978888629363.3639768161279133.07605789629345.534808486
1279203.58049899629308.8593015721279386.15582402629246.209203395
#Sta/Elev= 30
9758.391177.60559764.603176.2933 9781.61174.1651 9805.42169.59179815.624166.8429
9822.427164.16199836.032161.21379842.835158.10079853.118154.69769869.641151.5858
9887.611147.42349904.858144.41979915.206 143.3069925.662142.86569961.025 143.985
9979.286144.10449994.278 143.03410005.56 142.73110009.36  143.2110016.95145.1788
10020.75145.825710045.89147.587310070.37150.521310082.91151.444710091.28152.4289
10131.51159.385310147.03161.106210191.91 168.55610222.99 174.70210241.63  180.05
#Mann= 3 , 0 , 0
9758.391    0.12       09758.391    0.12       010241.63    0.12       0
#XS Ineff= 2 , 0
       0                               0
Bank Sta=9758.391,10241.63
Exp/Cntr=0.3,0.1

Type RM Length L Ch R = 1 ,4890.874,181.989400,181.989400,181.989400
XS GIS Cut Line= 6
1278983.65863134629546.5308006821279180.98284934 629511.12171473
 1279209.9916765629503.0304844351279244.44846569629487.829391103
1279278.77163905629477.2395496581279470.81561299629434.296275835
#Sta/Elev= 30
9749.502146.93489767.068144.38279787.025141.93569820.287139.30739860.207133.5537
9886.947131.43899900.316 130.9719913.686131.17259923.713130.91159953.866128.6501
9984.728130.140810006.29129.810310009.87130.050410023.94 133.48110047.98137.3693
10078.43144.2589 10095.3146.584110102.04  147.8210108.79149.590610118.91151.5889
10132.36155.783710145.79157.9064 10152.5159.618410169.28165.913210179.34168.3685
10192.77172.2209 10212.9178.853210226.33184.655710239.75189.705910250.51194.2006
#Mann= 3 , 0 , 0
9749.502    0.12       09749.502    0.12       010250.51    0.12       0
#XS Ineff= 2 , 0
       0                               0
Bank Sta=9749.502,10250.51
Exp/Cntr=0.3,0.1

Type RM Length L Ch R = 1 ,4708.885,181.989400,181.989400,181.989400
XS GIS Cut Line= 6
1278991.11610587629675.6350310991279108.16032305629671.057761066
1279230.12336093629675.2972998141279323.68802271629672.693294025
 1279397.8312421629668.6021379111279496.58791281629659.735401357
#Sta/Elev= 30
9746.897125.8676 9773.19125.97989796.173124.3716 9822.44124.7041 9832.29124.5342
9838.856 124.1439858.556123.90199878.246122.56089920.909118.7439 9953.76 117.753
9976.756117.66349996.462116.757110012.88117.274610026.01118.684510039.13119.4185
 10045.7120.115810065.39123.060310071.95124.4177 10081.8125.9268 10104.8131.6048
10124.51137.803210144.23143.4463 10150.8144.645710154.09145.490110163.97149.1453
10177.15153.5809 10203.5162.976310219.97169.378610226.56171.526810253.11182.9997
#Mann= 3 , 0 , 0
9746.897    0.12       09746.897    0.12       010253.11    0.12       0
#XS Ineff= 2 , 0
       09867.075                       0
Bank Sta=9746.897,10253.11
Exp/Cntr=0.3,0.1

Type RM Length L Ch R = 1 ,4526.895,181.989500,181.989500,181.989500
XS GIS Cut Line= 6
1278847.76645198629802.1686647981279156.36020198629859.460331455
1279232.31051272 629853.538246051279277.96703854629832.066611156
1279320.20205882629819.4755947741279385.02142799629809.288392752
#Sta/Elev= 30
 9588.16119.34419600.509118.0307 9610.52  116.339633.878114.6588  9653.9111.3476
9680.595110.7001 9707.29108.52079727.311108.58799757.343  110.459770.691110.1237
9787.376110.55559800.723110.03229807.397110.26349814.071110.91889834.092109.8014
9867.461110.35859884.146109.47339897.493109.3944  9917.3107.96739930.464107.8825
9950.208107.05559966.662  107.529983.646106.65819994.583107.266910016.32107.2117
10047.75 110.253 10068.3114.069410098.32120.880310124.89127.987310138.35132.2049
#Mann= 3 , 0 , 0
 9588.16  0.0789       0 9588.16  0.0789       010138.35  0.0789       0
#XS Ineff= 2 , 0
       09886.976                       0
Bank Sta=9588.16,10138.35
Exp/Cntr=0.3,0.1

Type RM Length L Ch R = 1 ,4344.906,181.989400,181.989400,181.989400
XS GIS Cut Line= 6
1278855.57895195629916.7519981271279093.86020198629974.043664783
1279211.20498848630006.5829281211279343.43727198630047.882378504
1279425.18491006630063.8250071851279515.59528896630075.899454191
#Sta/Elev= 30
9587.557112.83799604.158111.12239619.005108.84779652.748105.97839672.994103.4014
9723.60999.162729740.48199.016959750.60497.951829757.35398.621679774.22498.95475
9791.096100.01789824.839100.44659858.963102.10099900.04899.157699944.03899.03565
9968.03498.48378 9992.2997.1058910006.1996.7301910023.5796.88887 10037.496.24295
10064.5897.8797710084.9699.6266810108.49   104.110118.52105.134110151.95110.4481
10181.97117.185910195.21118.778810218.38126.025410244.86131.810710267.55138.5134
#Mann= 3 , 0 , 0
9587.557    0.12       09587.557    0.12       010267.55    0.12       0
#XS Ineff= 2 , 0
       09875.142        10065.97       0
Bank Sta=9587.557,10267.55
Exp/Cntr=0.3,0.1

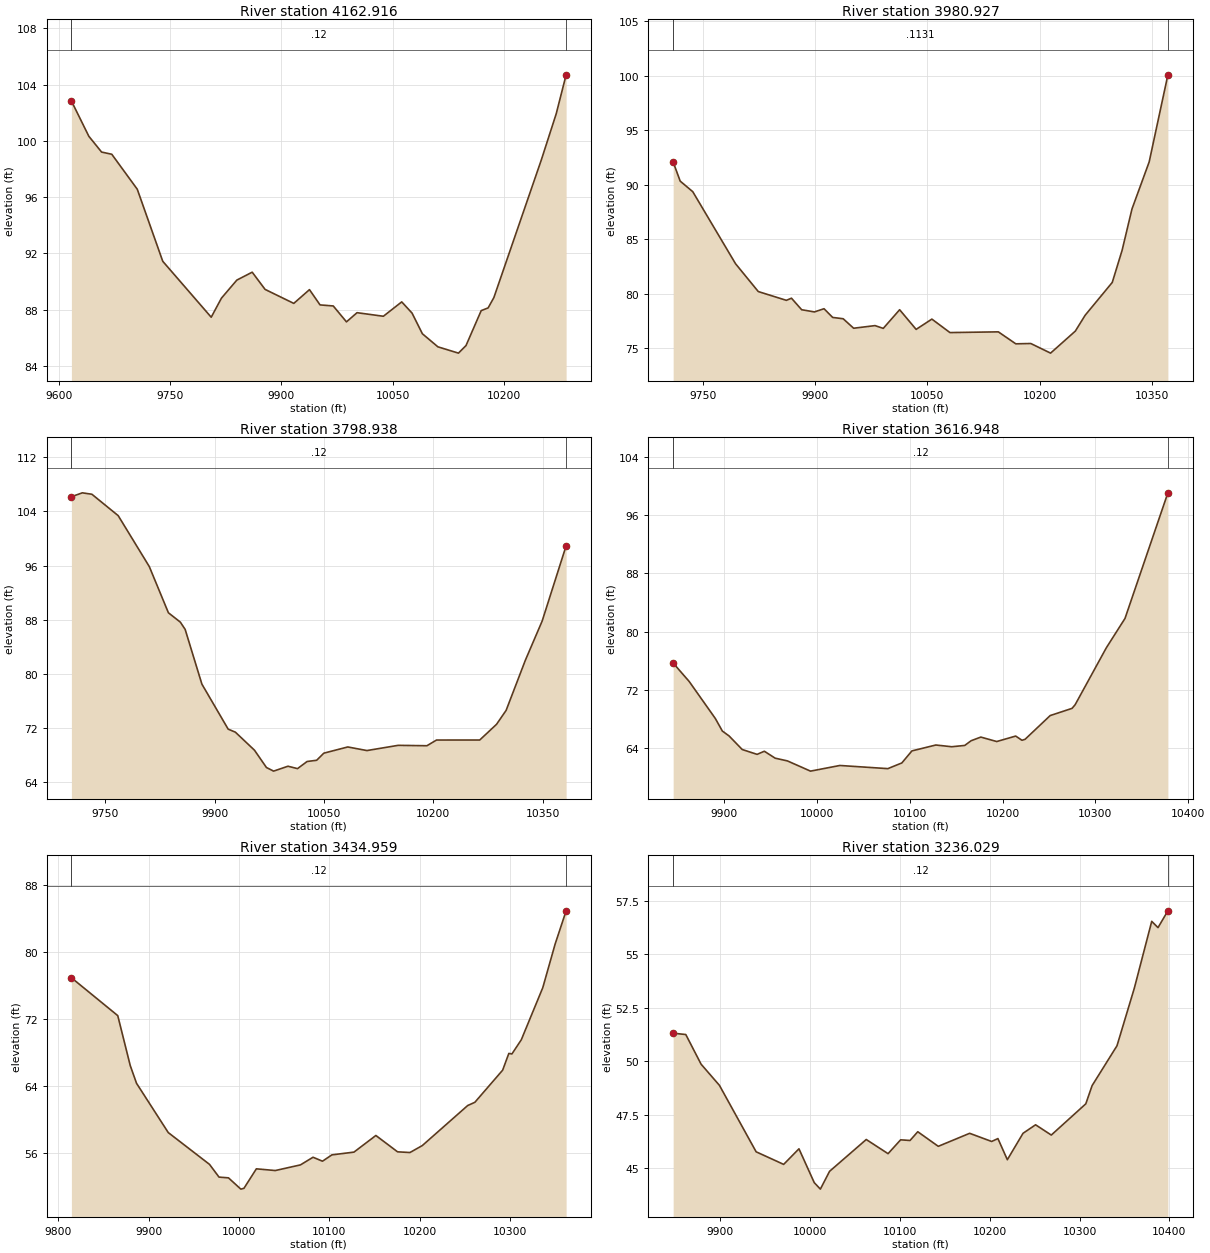
Type RM Length L Ch R = 1 ,4162.916,181.989400,181.989400,181.989400
XS GIS Cut Line= 6
1278824.32895195 630066.491581441279067.37077746630142.241457954
1279237.15761581630210.7962185441279305.94193563630235.200651348
1279379.13860926630255.5995305181279457.00069067630271.175234199
#Sta/Elev= 30
9617.236102.83419640.721100.32189657.87799.198279671.60299.042499705.91496.55555
9740.22591.430519805.47687.451059819.27288.808829839.96690.09142 9860.6690.65403
9878.01589.428919916.64388.434699937.76489.412489951.99488.326659969.78288.25189
9987.56987.1202310001.7987.7729410037.2687.5198710061.9588.5413810075.8887.74428
 10089.886.2728910110.6985.3446810138.3184.8968810148.5385.4366510168.96 87.9195
10178.2788.1118110185.9988.8437710249.88 98.636210269.95101.919910283.31104.6924
#Mann= 3 , 0 , 0
9617.236    0.12       09617.236    0.12       010283.31    0.12       0
#XS Ineff= 2 , 0
       09900.389         10154.1       0
Bank Sta=9617.236,10283.31
Exp/Cntr=0.3,0.1

Type RM Length L Ch R = 1 ,3980.927,181.989400,181.989400,181.989400
XS GIS Cut Line= 6
1278837.61624286630270.476901129 1279025.5146319630318.177872628
1279155.05346802630374.700512588 1279212.5610905630393.501024708
1279291.38923779 630410.190456481279475.37061867630428.470748127
#Sta/Elev= 30
9710.11692.063919719.51590.313579736.32989.34283  9793.582.736359823.91480.18149
9861.46579.376289868.29279.571789881.94778.512229899.01678.313989911.81178.60561
9923.40477.806179937.41677.686729951.42776.81636 9980.0577.057099991.018  76.802
10012.9178.5132810034.9776.7108510056.0477.65365 10080.2 76.417610144.87 76.4842
10168.2475.3853710188.2675.4152710214.73 74.532410247.8176.5525410260.9878.00973
 10297.281.0189410310.3783.9669310323.54 87.752510346.5892.0784110371.58100.0648
#Mann= 3 , 0 , 0
9710.116  0.1131       09710.116  0.1131       010371.58  0.1131       0
#XS Ineff= 2 , 0
       09929.256        10145.99       0
Bank Sta=9710.116,10371.58
Exp/Cntr=0.3,0.1

Type RM Length L Ch R = 1 ,3798.938,181.989500,181.989500,181.989500
XS GIS Cut Line= 6
1278792.40071562630536.5951074061278890.95495877630536.823565885
1279090.06390202 630534.239119441279143.99566263630533.499452174
1279205.56440666630529.766927674 1279470.1622853630506.595748127
#Sta/Elev= 30
 9703.32106.17889718.334106.75779731.458106.54719767.547 103.3829810.19895.85997
9836.44789.025859852.85387.637519859.41586.569419882.38378.480959918.47571.81882
9928.31971.377829954.56868.709549970.97366.151079980.81665.61627 10000.566.34129
10013.6365.9862810026.7567.0388410039.88 67.220110049.72 68.271410082.5869.18945
10108.8768.6564810151.6769.4286610191.1969.3690610204.3770.2123510263.6570.21421
 10286.772.5334310299.8874.5959810326.2281.9918910349.2887.7859910382.2398.93029
#Mann= 3 , 0 , 0
 9703.32    0.12       0 9703.32    0.12       010382.23    0.12       0
#XS Ineff= 2 , 0
       09927.242        10105.42       0
Bank Sta=9703.32,10382.23
Exp/Cntr=0.3,0.1

Type RM Length L Ch R = 1 ,3616.948,181.989400,181.989400,181.989400
XS GIS Cut Line= 6
1279011.37989441630781.5514318791279085.83960801630747.143593445
1279185.91239285630668.4238864631279250.69836804630634.486122116
1279322.96789461630610.0051719551279492.29770198630571.699914783
#Sta/Elev= 30
9845.15175.659039862.37273.130449890.56468.032699898.16566.296739905.314 65.6357
9919.55463.759859935.569 63.09179943.37163.522819955.07362.566339968.22362.19246
9993.12160.7855710024.7461.5629610076.4161.1286610091.4861.9101710102.3563.56791
10128.1364.3796510145.2364.1409610159.2264.3206410166.22 64.974110176.5865.47103
10193.7164.8581210214.14 65.611410220.9165.0300810224.2965.17091 10251.368.43133
10274.8169.4203510278.1769.9220210311.7677.7534710331.9181.80467 10378.199.08602
#Mann= 3 , 0 , 0
9845.151    0.12       09845.151    0.12       0 10378.1    0.12       0
#XS Ineff= 2 , 0
       09932.824        10097.75       0
Bank Sta=9845.151,10378.1
Exp/Cntr=0.3,0.1

Type RM Length L Ch R = 1 ,3434.959,198.929900,198.929900,198.929900
XS GIS Cut Line= 6
1279050.67759949630920.475992858  1279117.076491 630898.71040915
1279210.92895553630863.060981184 1279241.2535519630853.960719451
 1279361.1545988630811.3248901671279570.42270198 630750.08533144
#Sta/Elev= 30
9814.67776.91103 9865.9672.378939879.77166.403149886.71164.285399921.80658.38821
9967.43154.583589977.959 53.05889988.40952.9699810002.09 51.620710005.5251.71621
10019.28  54.04910040.1853.8441910068.03   54.5210081.9655.4345210092.4154.96239
10102.8555.7195310127.2356.0489710151.4858.0384210175.4656.0827410189.1656.00075
10202.8756.8360710253.02  61.62110260.9862.0104810291.7165.8561410298.5467.85769
10301.9567.7954310312.3269.4873810336.0975.7219510349.7580.9410510361.9284.91768
#Mann= 3 , 0 , 0
9814.677    0.12       09814.677    0.12       010361.92    0.12       0
#XS Ineff= 2 , 0
       09919.369        10077.37       0
Bank Sta=9814.677,10361.92
Exp/Cntr=0.3,0.1

Type RM Length L Ch R = 1 ,3236.029,0.000000,0.000000,0.000000
XS GIS Cut Line= 3
1279128.51028883631088.5518753081279342.05195549631030.392153084
1279651.07973328630918.412986428
#Sta/Elev= 30
9848.25651.31976  9862.351.257519879.30149.870759899.70348.880659940.508 45.7725
9971.11145.184579988.11245.9132710005.1144.3317210011.9144.0273810022.1244.85881
10062.92  46.34810087.17 45.685510101.1346.33277 10111.646.3025110120.1946.71085
10143.0146.02917 10177.946.6378910202.3346.2557810209.3146.3920410219.7845.40285
10237.2246.6386110251.1847.0359410268.6346.5557310307.0248.01731   1031448.86749
10341.6850.7321210360.9453.42281 10380.356.5498610387.2856.2568710398.2757.04239
#Mann= 3 , 0 , 0
9848.256    0.12       09848.256    0.12       010398.27    0.12       0
#XS Ineff= 2 , 0
       0 9917.97        10084.62       0
Bank Sta=9848.256,10398.27
Exp/Cntr=0.3,0.1